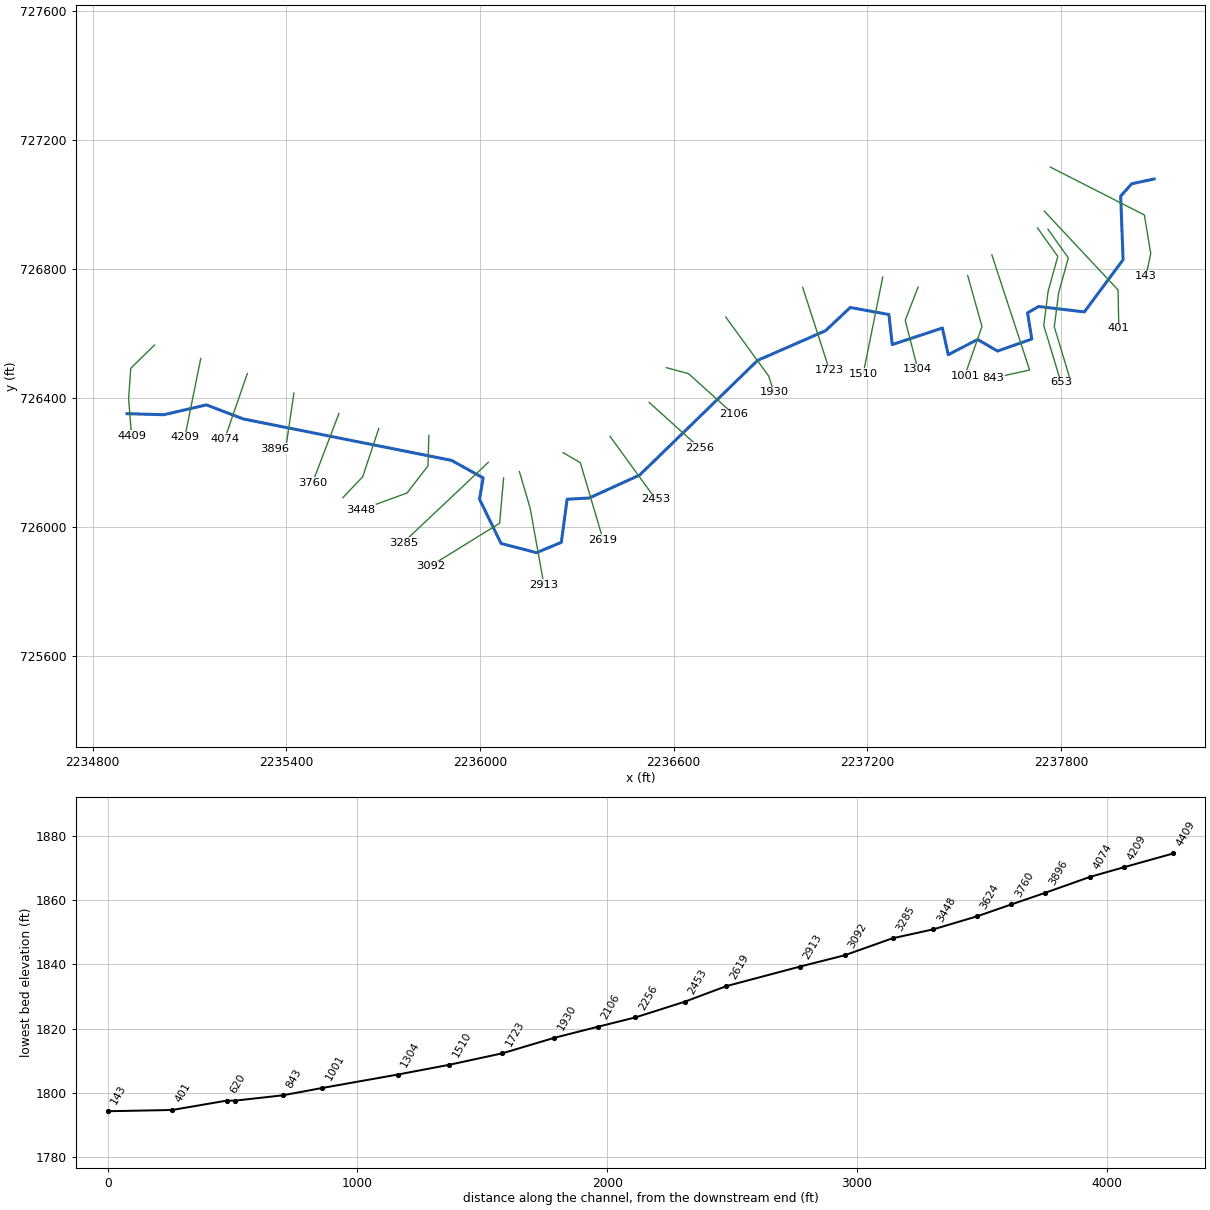
--- LAURELRN3.prj (project) ---

Proj Title=LAURELRN3
Current Plan=p01
Default Exp/Contr=0,0
English Units
Geom File=g01
Flow File=f01
Plan File=p01
BEGIN DESCRIPTION:
---------- MODELED AS PART OF WVEMD CTP PROGRAM, 2023----------
Stream Name: Laurel Run (III)
Flood Zone:  AFH
Upshur County, WV
HEC-RAS Version: RAS 6.3
Vertical Datum: NAVD88
Projection: NAD 1983 StatePlane West Virginia S FIPS 4702 (US Feet)
Terrain: 1-meter LIDAR (FEMA Region III 3DEP collected 2016-2018)
Land Use: 2019 NLCD
Hydrologic Method:
WV SIR2010-5033 regression equations
Additional Model Notes:
None
END DESCRIPTION:
DSS Export Rating Curves= 0
DSS Export Rating Curve Sorted= 0
DSS Export Volume Flow Curves= 0
DXF OffsetX= 0
DXF OffsetY= 0
DXF ScaleX= 0
DXF ScaleY= 0

--- LAURELRN3.p01 (plan) ---

Plan Title=Floodplain
Program Version=6.31
Short Identifier=Floodplain
Geom File=g01
Flow File=f01
Subcritical Flow
K Sum by GR= 0
Std Step Tol= 0.01
Critical Tol= 0.01
Num of Std Step Trials= 20
Max Error Tol= 0.3
Flow Tol Ratio= 0.001
Split Flow NTrial= 30
Split Flow Tol= 0.02
Split Flow Ratio= 0.02
Log Output Level= 0
Friction Slope Method= 1
Unsteady Friction Slope Method= 2
Unsteady Bridges Friction Slope Method= 1
Parabolic Critical Depth
Global Vel Dist= 0 , 0 , 0
Global Log Level= 0
CheckData=True
Encroach Param=-1 ,0,0, 0
Mapping Interval=1HOUR
Computation Time Step Use Courant=        0
Computation Time Step Use Time Series=    0
Computation Time Step Count To Double=0
Computation Time Step Max Doubling=0
Computation Time Step Max Halving=0
Computation Time Step Residence Courant=0
Run HTab= 0
Run UNet= 0
Run Sediment= 0
Run PostProcess= 0
Run WQNet= 0
Run RASMapper=-1
UNET Theta= 0
UNET Theta Warmup= 0
UNET ZTol= 0
UNET ZSATol= 0
UNET MxIter= 0
UNET Max Iter WO Improvement= 0
UNET MaxInSteps= 0
UNET DtIC= 0
UNET DtMin= 0
UNET MaxCRTS= 0
UNET WFStab= 0
UNET SFStab= 0
UNET WFX= 1
UNET SFX= 1
UNET Gravity=32.17405
UNET 1D Methodology=Finite Difference
UNET DSS MLevel= 1
UNET Pardiso=0
UNET DZMax Abort= 0
UNET Use Existing IB Tables= 0
UNET Froude Reduction=False
UNET Froude Limit= 0
UNET Froude Power= 0
UNET D1 Cores= 0
UNET WindReference=Eulerian
UNET WindDragFormulation=Hsu (1988)
UNET D2 Coriolis=0
UNET D2 Cores= 0
UNET D2 Theta= 1
UNET D2 Theta Warmup= 1
UNET D2 Z Tol= 0.01
UNET D2 Volume Tol= 0.01
UNET D2 Max Iterations= 20
UNET D2 Equation= 0
UNET D2 RampUpFraction=0.1
UNET D2 TimeSlices= 1
UNET D2 Turbulence Formulation=Non-Conservative (original)
UNET D2 Eddy Viscosity=0.3
UNET D2 Transverse Eddy Viscosity=0.1
UNET D2 Smagorinsky Mixing=0
UNET D2 BCVolumeCheck=0
UNET D2 Cores=0
UNET D2 SolverType=PARDISO (Direct)
UNET D2 Minimum Iterations= 3
UNET D2 Maximum Iterations= 30
UNET D2 Restart Number= 10
UNET D2 Relaxation Coeff=1.3
UNET D2 SOR Precondition Iterations= 10
UNET D2 ILUT Maximum Fill= 8
UNET D2 ILUT Tolerance=1E-08
UNET D2 Convergence Tolerance=0.00001
UNET D1D2 MaxIter= 0
UNET D1D2 ZTol=0.01
UNET D1D2 QTol=0.1
UNET D1D2 MinQTol=1
Write IC File= 0
Write IC File at Fixed DateTime=0
Write IC File at Sim End=0
Echo Input=False
Echo Parameters=False
Echo Output=False
Write Detailed= 0
HDF Write Warmup=0
HDF Write Time Slices=0
HDF Flush=0
HDF Compression= 1
HDF Chunk Size= 1
HDF Spatial Parts= 1
HDF Use Max Rows=0
HDF Fixed Rows= 1
Calibration Method= 0
Calibration Iterations= 20
Calibration Max Change=0.05
Calibration Tolerance=0.2
Calibration Maximum=1.5
Calibration Minimum=0.5
Calibration Optimization Method= 1
WQ AD Non Conservative
WQ ULTIMATE=-1
WQ Max Comp Step=1HOUR
WQ Output Interval=15MIN
WQ Output Selected Increments= 0
WQ Create Restart=0
WQ Fixed Restart=0
WQ System Summary=0
WQ Write To DSS=0
Sorting and Armoring Iterations= 10
XS Update Threshold= 0.02
Bed Roughness Predictor= 0
Hydraulics Update Threshold= 0.02
Energy Slope Method= 1
Volume Change Method= 1
Sediment Retention Method= 0
Sediment TS Multiplier= 1
Warm Up Method= 0
XS Weighting Method= 0
Number of US Weighted Cross Sections= 1
Number of DS Weighted Cross Sections= 1
Upstream XS Weight=0
Main XS Weight=1
Downstream XS Weight=0
Number of DS XS's Weighted with US Boundary= 1
Upstream Boundary Weight= 1
Weight of XSs Associated with US Boundary= 0
Number of US XS's Weighted with DS Boundary= 1
Downstream Boundary Weight= 0.5
Weight of XSs Associated with DS Boundary= 0.5
Percentile Method= 0
Sediment Output Level= 3
Mass or Volume Output= 0
Output Increment Type= 1
Profile and TS Output Increment= 1
Transport Output Increment 1
XS Output Flag= 0
XS Output Increment= 10
Read HDF5 Sediment Hotstart= 0
Sediment Hotstart Type= 0
Write Gradation File= 0
Read Gradation Hotstart= 0
Write HDF5 File= 1
Write Binary Output= 1
Write DSS Sediment File= 0
DSS Sediment Output Type= 1
SV Curve= 0
Specific Gage Flag= 0
Subcell Erosion Methods= 0
Subcell Deposition Methods= 0
Advection Scheme= 1
Matrix Solver= 0
Implicit Weighting Factor= 1
Maximum Outer Loop Convergence Iterations= 5
Convergence Maximum Absolute= 0.001
Convergence RMSE= 0.0001
Grain Fractions Max Abs Error= 0.001
Max Subgrid Regions= 1
Max Subgrid Length Scale= 3.402823E+38
Initial Layer Thickness= 3.402823E+38
Min Layer Thickness= 3.402823E+38
Max Layer Thickness= 3.402823E+38
Number of Layers= 5

--- LAURELRN3.f01 (steady flow) ---

Flow Title=Flows
Program Version=6.31
Number of Profiles= 1
Profile Names=01pct
River Rch & RM=LAURELRN3,Main,4409
     477
Boundary for River Rch & Prof#=LAURELRN3,Main            , 1
Up Type= 0
Dn Type= 3
Dn Slope=0.00643
DSS Import GetInterval= 0
DSS Import GetPeak= 0
DSS Import FillOption= 0

--- LAURELRN3.g01 (geometry) ---

Geom Title=Geometry
Program Version=6.31

River Reach=LAURELRN3       ,Main
Reach XY= 30
 2234906.3067289726352.3152309952235020.50000003726349.107000008
2235152.33599998726379.5260000082235266.51600003726336.001000017
2235911.78600004726207.6280000062236009.82600001726153.341999993
2235998.66599999 726087.267000022236065.37100001725950.137000009
2236175.17200002725921.6070000082236252.12100004725953.542999998
2236270.00600003726087.2099999932236338.60000001      726091.044
2236494.73100004726162.041999996     2236860.477726517.542999998
     2237070.836726609.3730000112237147.44200002726681.371999994
2237267.20200001726659.6519999952237277.58900002 726566.36300002
2237432.86200002726617.7580000162237451.06200001726535.056000009
2237542.06200004726582.2450000052237603.81599998726546.331000015
     2237709.897726583.6470000152237696.87699999726664.603000015
     2237731.016726684.4620000122237872.78200004726667.665000007
2237992.82699999726829.3470000182237985.38699999727026.657000005
2238019.84100001727064.8030000182238088.80686951727079.568867922

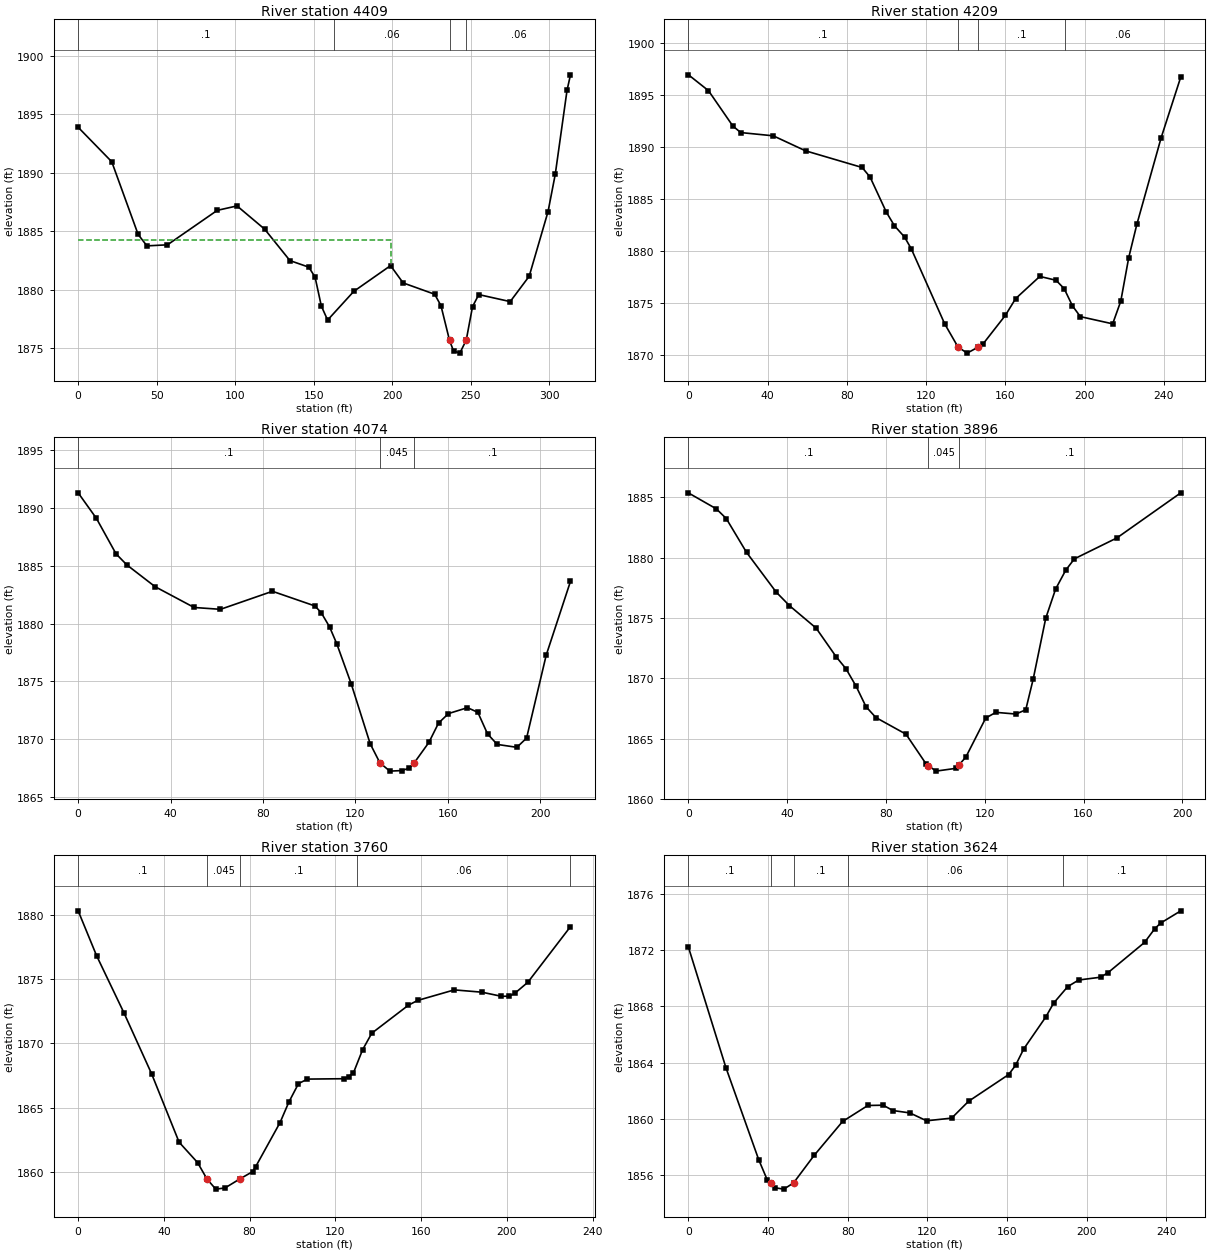
Type RM Length L Ch R = 1 ,4409    ,199.7,199.7,199.7
XS GIS Cut Line= 4
2234991.42867859726565.0291497972234917.83413278726492.915971462
2234911.22297138726398.0594016152234920.42469508726282.945234397
#Sta/Elev= 30
       0 1893.89    21.4 1890.94    38.2 1884.72    43.8 1883.74    56.9 1883.83
    88.6 1886.78   101.2 1887.16   118.8 1885.17   134.9 1882.48   146.9 1881.92
   150.9 1881.07   154.9 1878.59   158.9 1877.39   175.6 1879.85     199 1882.05
     207 1880.57   227.1  1879.6   231.1 1878.62  236.56 1875.65   239.1 1874.75
   243.1 1874.56   247.2 1875.67   251.2 1878.54   255.2 1879.57   275.2 1878.97
   287.3 1881.14   299.3 1886.67   303.9 1889.86   311.4 1897.05   313.6 1898.38
#Mann= 4 ,-1,0
       0      .1       0  163.04     .06       0  236.56    .045       0
   247.2     .06       0
#XS Ineff= 2 , 0
          199.53  1884.2
Permanent Ineff=
       F       F
Bank Sta=236.56,247.2
XS Rating Curve= 0 ,0
Exp/Cntr(USF)=0,0
Exp/Cntr=0.3,0.1

Type RM Length L Ch R = 1 ,4209    ,136.2,134.9,133.9
XS GIS Cut Line= 2
2235134.76128269726523.1042447542235085.48158523726279.406014857
#Sta/Elev= 30
       0 1896.92    10.1  1895.4    22.4 1892.01    26.4 1891.38    42.8 1891.07
    59.1 1889.63    87.7 1888.03    91.7 1887.11    99.9 1883.75     104 1882.44
   109.1 1881.36   112.5 1880.23   129.4 1873.02  136.09 1870.81   140.7 1870.22
   146.4 1870.81   148.9 1871.14     160 1873.84   165.2 1875.45   177.4 1877.58
   185.6 1877.21   189.7 1876.41   193.9 1874.75   197.9 1873.72   214.2 1873.03
   218.3 1875.21   222.3 1879.38   226.4 1882.57   238.7  1890.9   248.6 1896.72
#Mann= 4 ,-1,0
       0      .1       0  136.09    .045       0   146.4      .1       0
     190     .06       0
Bank Sta=136.09,146.4
XS Rating Curve= 0 ,0
Exp/Cntr(USF)=0,0
Exp/Cntr=0.3,0.1

Type RM Length L Ch R = 1 ,4074    ,176.1,178.3,180.7
XS GIS Cut Line= 2
2235279.06407168726476.6503253172235209.41093218726275.205873152
#Sta/Elev= 30
       0 1891.31     7.9  1889.1    16.4 1886.03    21.1 1885.07    33.3 1883.19
    50.2 1881.39    61.6 1881.23    84.1 1882.79   102.5 1881.52   105.2 1880.94
   108.8 1879.72   111.9 1878.27   118.2 1874.78   126.4  1869.6   130.6 1867.95
   134.9 1867.23   140.2 1867.28   143.4  1867.5   145.51867.955   151.8 1869.71
     156 1871.39   160.3 1872.21   168.5 1872.72     173 1872.32   177.2 1870.45
   181.4 1869.54   189.9 1869.29   194.1 1870.09   202.6 1877.27   213.1 1883.65
#Mann= 3 ,-1,0
       0      .1       0   130.6    .045       0   145.5      .1       0
Bank Sta=130.6,145.5
XS Rating Curve= 0 ,0
Exp/Cntr(USF)=0,0
Exp/Cntr=0.3,0.1

Type RM Length L Ch R = 1 ,3896    ,138,136.3,132.4
XS GIS Cut Line= 3
2235423.49633931726416.3130738272235399.98384804726257.193656185
2235363.89490796726243.523603123
#Sta/Elev= 30
       0 1885.35    11.3 1884.03    15.3 1883.23    23.5 1880.43    35.5 1877.14
    40.9 1876.01    51.7 1874.15    59.8 1871.78    63.8 1870.78    67.9 1869.33
    71.9 1867.64    75.9 1866.74    88.1 1865.36    96.2 1862.91   97.191862.759
   100.2  1862.3   108.3 1862.53  109.391862.781   112.3 1863.45   120.4  1866.7
   124.5 1867.17   132.6 1867.03   136.6 1867.38   139.6 1869.91   144.7 1874.97
   148.7 1877.39   152.8 1878.95   156.3 1879.89   173.5 1881.62   199.4 1885.36
#Mann= 3 ,-1,0
       0      .1       0   97.19    .045       0  109.39      .1       0
Bank Sta=97.19,109.39
XS Rating Curve= 0 ,0
Exp/Cntr(USF)=0,0
Exp/Cntr=0.3,0.1

Type RM Length L Ch R = 1 ,3760    ,135.6,136.3,137.3
XS GIS Cut Line= 2
2235562.94721543 726353.217392732235481.26442923 726138.54692983
#Sta/Elev= 30
       0 1880.31     8.6 1876.82    21.4 1872.36    34.3 1867.62    47.1 1862.31
    55.7 1860.73   60.131859.439    64.2 1858.66    68.5 1858.75    75.51859.459
    81.4 1860.02    82.8  1860.4    94.2 1863.84    98.3 1865.43   102.8 1866.87
     107 1867.22   124.2 1867.25   126.2 1867.42   128.4 1867.69   132.7  1869.5
     137 1870.79   154.1 1872.97   158.4 1873.34   175.5 1874.16   188.4 1873.98
   197.5 1873.66   201.2 1873.67   203.7 1873.89   209.8 1874.75   229.7 1879.08
#Mann= 5 ,-1,0
       0      .1       0   60.13    .045       0    75.5      .1       0
     130     .06       0  229.69      .1       0
Bank Sta=60.13,75.5
XS Rating Curve= 0 ,0
Exp/Cntr(USF)=0,0
Exp/Cntr=0.3,0.1

Type RM Length L Ch R = 1 ,3624    ,172,175.8,179
XS GIS Cut Line= 3
2235686.48399125726306.6379526662235636.52922944726156.773667246
2235575.09837371726091.967489766
#Sta/Elev= 30
       0 1872.21    18.8 1863.64    35.3 1857.07    39.5 1855.66    41.41855.393
    43.7 1855.07    47.9 1854.98   52.76 1855.42    63.1 1857.38    77.4  1859.8
    90.1 1860.94    97.8 1860.96   102.7 1860.58   111.2 1860.41   119.6 1859.85
   132.2 1860.04   140.7 1861.24   160.8 1863.14   164.3  1863.8   168.4 1864.97
   179.5 1867.25   183.4 1868.23   190.5 1869.41     196 1869.88     207 1870.08
   210.8 1870.41   229.1 1872.56   234.3 1873.55   237.2 1873.94   247.3 1874.81
#Mann= 5 ,-1,0
       0      .1       0    41.4    .045       0   52.76      .1       0
      80     .06       0  187.97      .1       0
Bank Sta=41.4,52.76
XS Rating Curve= 0 ,0
Exp/Cntr(USF)=0,0
Exp/Cntr=0.3,0.1

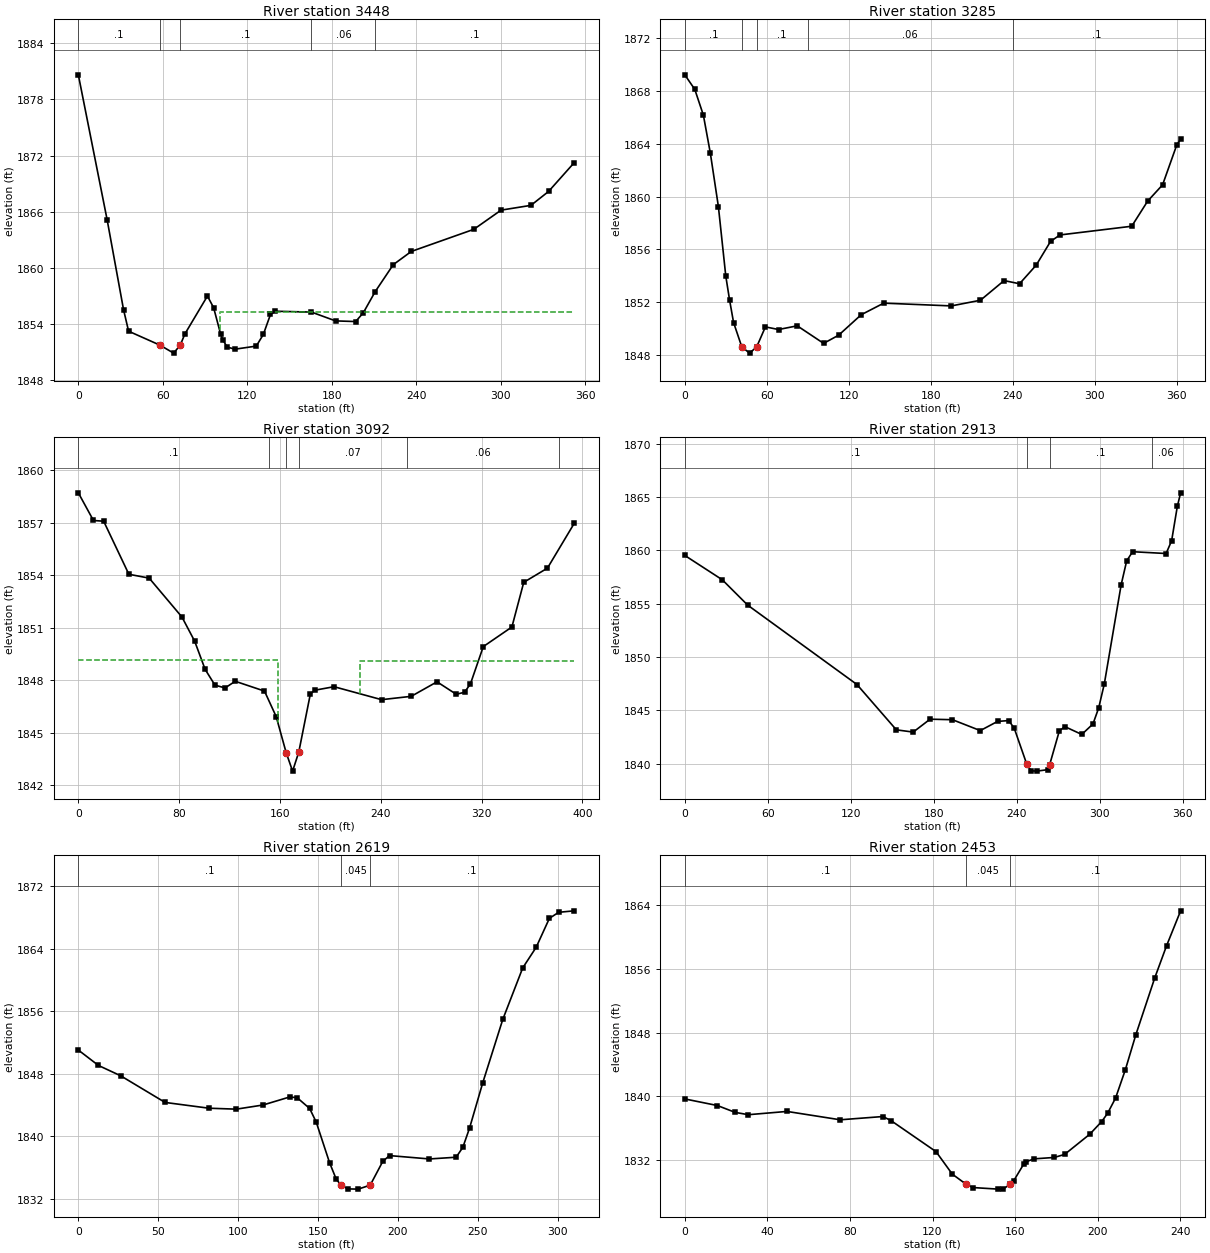
Type RM Length L Ch R = 1 ,3448    ,172.1,163,154.8
XS GIS Cut Line= 4
2235841.56286839726284.859436357 2235838.7848258726190.602218959
2235774.15282446726106.5735347542235631.43687755726054.577087665
#Sta/Elev= 30
       0 1880.61    20.5 1865.11    32.1 1855.56    35.7 1853.25      58 1851.76
    67.7 1850.91    72.41851.764    75.7 1852.96    91.7    1857    96.1 1855.76
   101.1 1852.93   102.9 1852.26   105.7 1851.56   111.2 1851.33   126.4 1851.66
   131.4  1852.9   136.5 1855.04     140 1855.38   165.6 1855.29   182.7 1854.35
     197 1854.28   202.4 1855.21   210.9 1857.48   223.7 1860.35   236.5 1861.76
   280.9 1864.12   300.3 1866.17   321.5 1866.68     334 1868.16   352.2 1871.23
#Mann= 5 ,-1,0
       0      .1       0      58    .045       0    72.4      .1       0
   165.6     .06       0   210.9      .1       0
#XS Ineff= 2 , 0
                          100.33         1855.28
Permanent Ineff=
       F       T
Bank Sta=58,72.4
XS Rating Curve= 0 ,0
Exp/Cntr(USF)=0,0
Exp/Cntr=0.3,0.1

Type RM Length L Ch R = 1 ,3285    ,194.3,192.4,192.6
XS GIS Cut Line= 2
2236026.04547429726201.6972643612235762.13142848725952.599445689
#Sta/Elev= 30
       0 1869.23     7.3 1868.13    13.6 1866.17    18.7 1863.29    24.6 1859.23
      30 1853.97    32.8 1852.14    35.7 1850.45   41.711848.606    47.4 1848.13
    52.6  1848.6      59 1850.12    68.6 1849.92    82.3  1850.2   101.6 1848.87
   112.6 1849.49   129.1 1851.04   145.6 1851.92   195.1 1851.71   216.4 1852.14
   233.7 1853.63     245 1853.39   257.2  1854.8   267.7  1856.6   274.6 1857.09
   327.1 1857.75   338.8 1859.66   349.7 1860.89   360.1 1863.92   362.9 1864.35
#Mann= 5 ,-1,0
       0      .1       0   41.71    .045       0    52.6      .1       0
      90     .06       0     240      .1       0
Bank Sta=41.71,52.6
XS Rating Curve= 0 ,0
Exp/Cntr(USF)=0,0
Exp/Cntr=0.3,0.1

Type RM Length L Ch R = 1 ,3092    ,164.4,179.2,192.4
XS GIS Cut Line= 3
2236073.29167165726153.1558288622236060.82023387726012.658081562
2235846.18150709  725879.9816411
#Sta/Elev= 30
       0 1858.71      12 1857.13    20.1 1857.09    40.1 1854.06    56.2 1853.84
    82.2 1851.62    92.3 1850.24   100.6 1848.63   108.4 1847.73   116.4 1847.57
   124.5 1847.95   147.7 1847.39     157 1845.93   164.91843.872     170 1842.82
   174.91843.905   184.1 1847.23   187.6 1847.44   202.9 1847.64   240.6  1846.9
   264.1 1847.09   284.6 1847.92   299.8 1847.21   306.4 1847.32   311.1  1847.8
   321.3 1849.93     344 1851.05   353.4  1853.6   372.2 1854.41   393.4 1856.96
#Mann= 6 ,-1,0
       0      .1       0  151.05     .07       0   164.9    .045       0
   174.9     .07       0  261.05     .06       0  381.05      .1       0
#XS Ineff= 2 , 0
          158.42 1849.15  223.87         1849.08
Permanent Ineff=
       F       F
Bank Sta=164.9,174.9
XS Rating Curve= 0 ,0
Exp/Cntr(USF)=0,0
Exp/Cntr=0.3,0.1

Type RM Length L Ch R = 1 ,2913    ,289.6,294,292
XS GIS Cut Line= 3
 2236122.1350077726172.8053674012236155.47151875726059.831635513
2236198.06817175725822.772001387
#Sta/Elev= 30
       0 1859.51    27.1 1857.23    45.5 1854.85   124.5 1847.41     153 1843.16
   165.2 1842.95   177.4 1844.16   193.6 1844.11   213.7 1843.09   226.2 1843.95
   234.3 1844.03   238.3  1843.3  247.391839.915   250.5 1839.32   254.6 1839.29
   262.7 1839.43   263.9  1839.9   270.9 1843.07   274.9 1843.46   287.1 1842.73
   295.2 1843.71   299.3  1845.2   303.4 1847.46   315.6 1856.77   319.6 1859.01
   323.9 1859.86   348.1 1859.69   352.1 1860.89   356.2  1864.1   358.6 1865.38
#Mann= 4 ,-1,0
       0      .1       0  247.39    .045       0   263.9      .1       0
  337.79     .06       0
Bank Sta=247.39,263.9
XS Rating Curve= 0 ,0
Exp/Cntr(USF)=0,0
Exp/Cntr=0.3,0.1

Type RM Length L Ch R = 1 ,2619    ,159.6,166.6,170.2
XS GIS Cut Line= 3
2236257.29497271726231.7781178192236311.00379606726200.293635162
2236381.38087494725962.307986839
#Sta/Elev= 30
       0 1851.01    12.6 1849.04    26.5 1847.72    54.3 1844.31    81.8 1843.57
    98.9 1843.45   115.6 1843.98   132.2    1845   136.9 1844.93   144.8 1843.54
   148.9 1841.81   157.3 1836.59   161.4 1834.52  164.511833.701   168.7 1833.25
   175.2 1833.22  182.73 1833.73   190.6 1836.77   194.8 1837.51   219.8 1837.08
   236.5  1837.3   240.7 1838.56   244.9 1841.02   253.2 1846.84   265.7 1854.92
   278.2 1861.52   286.6 1864.15   294.9 1867.86   300.7 1868.63   310.4 1868.82
#Mann= 3 ,-1,0
       0      .1       0  164.51    .045       0  182.73      .1       0
Bank Sta=164.51,182.73
XS Rating Curve= 0 ,0
Exp/Cntr(USF)=0,0
Exp/Cntr=0.3,0.1

Type RM Length L Ch R = 1 ,2453    ,190.2,197,197.8
XS GIS Cut Line= 2
2236403.09584432 726282.119501352236544.05578302 726087.65652023
#Sta/Elev= 30
       0 1839.69    15.8 1838.86    24.4    1838    30.8 1837.71    49.5 1838.12
    75.3 1837.07      96 1837.48     100 1836.95   121.7 1833.07   129.6 1830.24
  136.381828.955   139.5 1828.56   151.8 1828.36   154.3 1828.39  157.621828.959
   159.3 1829.39   164.2 1831.51   165.4  1831.8   169.1 1832.16     179 1832.34
     184 1832.72   196.2 1835.26   201.9 1836.83   204.8 1837.87   208.7 1839.81
   213.4 1843.34   218.5 1847.75   227.7 1854.92   233.4 1858.94   240.2 1863.32
#Mann= 3 ,-1,0
       0      .1       0  136.38    .045       0  157.62      .1       0
Bank Sta=136.38,157.62
XS Rating Curve= 0 ,0
Exp/Cntr(USF)=0,0
Exp/Cntr=0.3,0.1

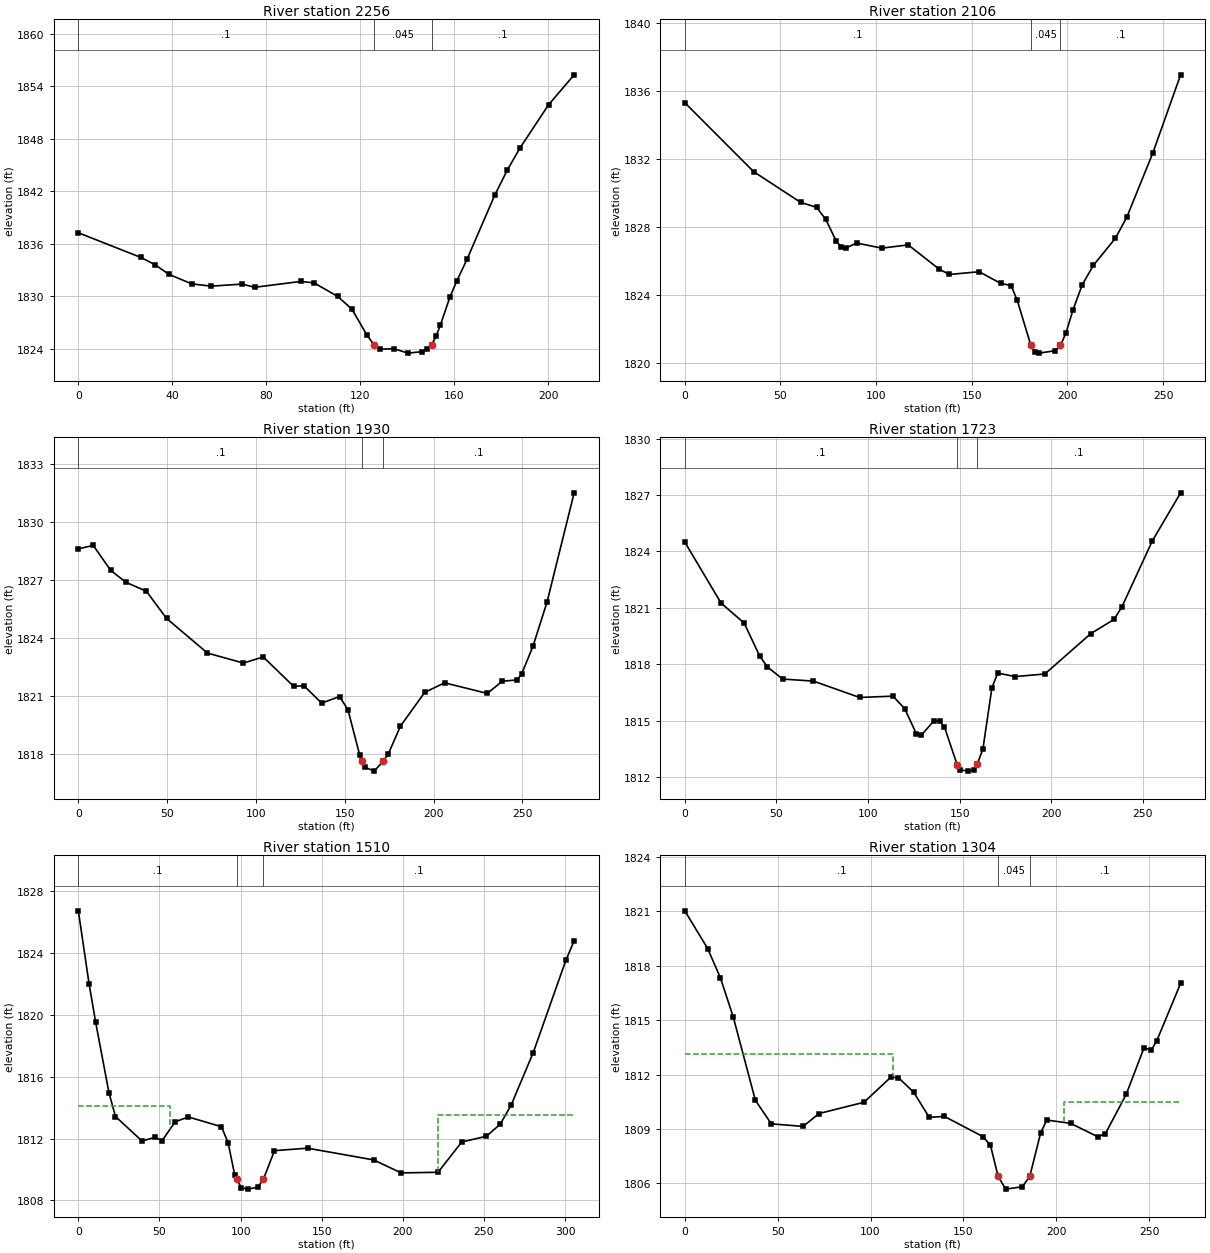
Type RM Length L Ch R = 1 ,2256    ,149,149.2,148.8
XS GIS Cut Line= 2
2236524.35416412726386.9534541352236681.31928645726245.891895226
#Sta/Elev= 30
       0 1837.26    26.6 1834.44    32.6 1833.61    38.6  1832.5    48.2 1831.42
    56.5 1831.15    69.7 1831.39      75 1831.02    94.6 1831.69   100.3 1831.53
   110.4 1829.97   116.4 1828.53   122.9 1825.52   125.8 1824.46   128.3 1823.93
   134.2    1824   140.3 1823.49   146.3 1823.66   148.4 1823.95  150.431824.458
   152.3 1825.47   154.1 1826.72   158.2 1829.96   161.1 1831.77   165.4 1834.22
   177.2 1841.56   182.6 1844.46     188 1846.98   200.1  1851.9     211 1855.33
#Mann= 3 ,-1,0
       0      .1       0   125.8    .045       0  150.43      .1       0
Bank Sta=125.8,150.43
XS Rating Curve= 0 ,0
Exp/Cntr(USF)=0,0
Exp/Cntr=0.3,0.1

Type RM Length L Ch R = 1 ,2106    ,178.2,176.4,173.8
XS GIS Cut Line= 3
2236577.64253384726494.8449050942236646.16758433726476.324621178
 2236785.9957279726350.386690548
#Sta/Elev= 30
       0 1835.33      36 1831.27    60.6 1829.46    68.9 1829.17    73.7 1828.46
    79.1  1827.2    81.7 1826.83    84.5 1826.79    89.8 1827.07     103 1826.77
   116.8 1826.96   132.9 1825.54   138.3 1825.22   153.9 1825.38   165.2 1824.69
   170.6 1824.57   173.8 1823.69  180.871821.066   183.3 1820.63   185.1 1820.59
   193.6 1820.73   196.4 1821.04   199.3 1821.79   202.9 1823.12   207.7  1824.6
   213.6 1825.76   225.1 1827.35   231.1  1828.6   244.6 1832.35   259.2 1836.97
#Mann= 3 ,-1,0
       0      .1       0  180.87    .045       0   196.4      .1       0
Bank Sta=180.87,196.4
XS Rating Curve= 0 ,0
Exp/Cntr(USF)=0,0
Exp/Cntr=0.3,0.1

Type RM Length L Ch R = 1 ,1930    ,210,206.8,203.2
XS GIS Cut Line= 3
2236761.48721885726651.9380688892236894.83326305726468.587258119
 2236910.6681058726418.582491546
#Sta/Elev= 30
       0 1828.61     8.4 1828.79    18.2  1827.5    26.8 1826.88    38.3 1826.42
    49.7 1825.01    72.7 1823.22      93  1822.7   104.1 1823.02   121.3 1821.49
     127 1821.53     137 1820.63   147.1 1820.97   151.8 1820.29   158.5 1817.92
  159.861817.626   161.4 1817.31   166.6 1817.11   171.6 1817.62   174.6 1818.01
   181.4 1819.44     195 1821.18   206.2 1821.68   230.3 1821.13   238.7 1821.76
   247.1 1821.83   249.6 1822.13     256 1823.57   263.9 1825.85   279.2 1831.51
#Mann= 3 ,-1,0
       0      .1       0  159.86    .045       0   171.6      .1       0
Bank Sta=159.86,171.6
XS Rating Curve= 0 ,0
Exp/Cntr(USF)=0,0
Exp/Cntr=0.3,0.1

Type RM Length L Ch R = 1 ,1723    ,218.6,212.8,203.7
XS GIS Cut Line= 2
2236999.83869994726743.9688909712237083.17997757726486.536944536
#Sta/Elev= 30
       0  1824.5    19.8 1821.25    32.4 1820.19    40.8 1818.45      45 1817.86
    53.4 1817.21    70.2  1817.1    95.4 1816.23   113.6  1816.3     120 1815.64
   126.4 1814.29   129.1 1814.22   135.9 1814.98   139.1 1814.96   141.7 1814.66
   148.6 1812.66   150.1 1812.39   154.3 1812.31   158.1 1812.37  159.611812.682
   162.7 1813.49   167.6 1816.74   170.8 1817.53   180.3 1817.34   196.5 1817.48
   221.6 1819.63   234.2 1820.38   238.4 1821.02   255.2 1824.57   270.6 1827.12
#Mann= 3 ,-1,0
       0      .1       0   148.6    .045       0  159.61      .1       0
Bank Sta=148.6,159.61
XS Rating Curve= 0 ,0
Exp/Cntr(USF)=0,0
Exp/Cntr=0.3,0.1

Type RM Length L Ch R = 1 ,1510    ,199.3,206.6,210.6
XS GIS Cut Line= 2
2237248.13625943726775.6705868352237187.54520711 726476.14500745
#Sta/Elev= 30
       0 1826.74     6.6 1822.03    10.7 1819.52    18.9 1814.96    22.9 1813.43
    39.3 1811.84    47.4 1812.09    51.5 1811.85    59.7 1813.09    67.8  1813.4
    88.2 1812.77    92.3 1811.74    96.4 1809.64   97.711809.375   100.5 1808.81
   104.6 1808.73   110.7 1808.86   114.1 1809.38   120.9 1811.22   141.3 1811.38
     182 1810.62     199 1809.78   221.7 1809.82   236.3 1811.78   251.5 1812.15
   260.1 1812.94   266.8 1814.18   280.4 1817.57   300.5 1823.54   305.6  1824.8
#Mann= 3 ,-1,0
       0      .1       0   97.71    .045       0   114.1      .1       0
#XS Ineff= 2 , 0
            56.6  1814.1   221.4         1813.55
Permanent Ineff=
       F       F
Bank Sta=97.71,114.1
XS Rating Curve= 0 ,0
Exp/Cntr(USF)=0,0
Exp/Cntr=0.3,0.1

Type RM Length L Ch R = 1 ,1304    ,304.7,303.2,300.3
XS GIS Cut Line= 3
2237357.58885092 726744.62053059 2237317.7702405726641.832954856
2237356.66283673726489.966626743
#Sta/Elev= 30
       0 1821.03    12.3 1818.95    19.2 1817.33    26.1 1815.17      38 1810.58
    46.6 1809.28    63.7 1809.14    72.3 1809.85    96.5 1810.47   110.9 1811.85
     115 1811.83   123.3 1811.02   131.6 1809.64   139.8 1809.69   160.5 1808.58
   164.6  1808.1   168.7 1806.39   172.8 1805.68   181.8 1805.81  185.811806.404
   191.6 1808.77   194.9 1809.49   207.7 1809.31   222.4 1808.57   226.5 1808.74
   237.7 1810.91   247.2 1813.45   251.3 1813.37   254.1 1813.85     267 1817.03
#Mann= 3 ,-1,0
       0      .1       0   168.7    .045       0  185.81      .1       0
#XS Ineff= 2 , 0
          111.93 1813.13  204.29         1810.49
Permanent Ineff=
       F       F
Bank Sta=168.7,185.81
XS Rating Curve= 0 ,0
Exp/Cntr(USF)=0,0
Exp/Cntr=0.3,0.1

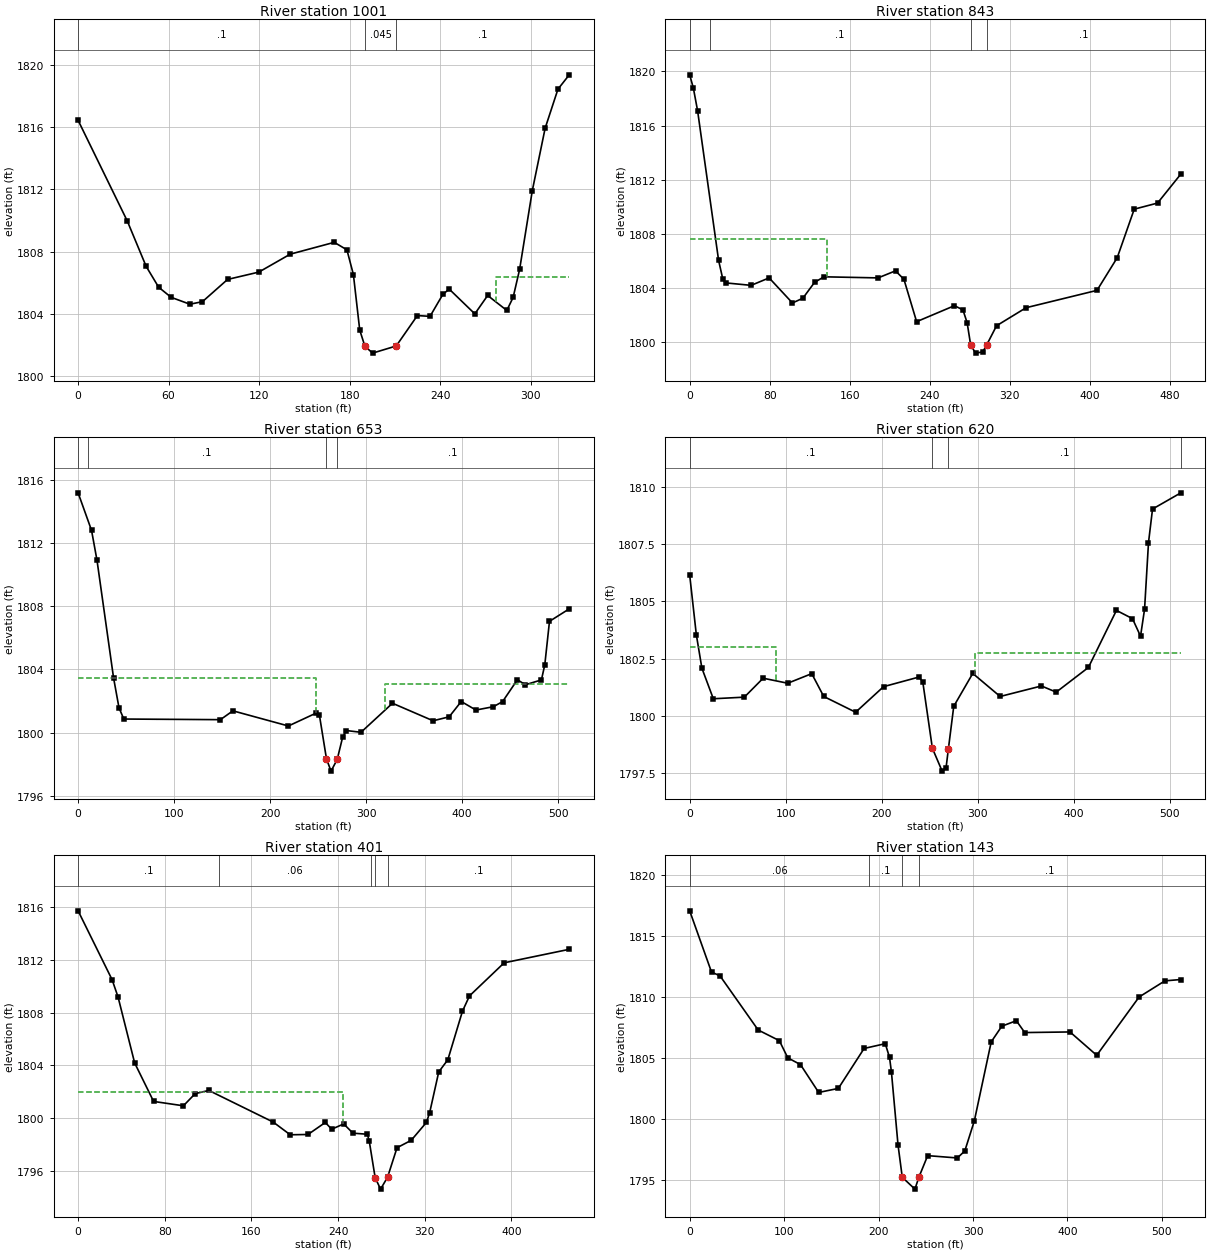
Type RM Length L Ch R = 1 ,1001    ,145,157.6,165.1
XS GIS Cut Line= 3
2237511.30926524726780.5735461952237555.56348365726622.308459989
2237502.30840725726470.043945773
#Sta/Elev= 30
       0 1816.43    32.6 1809.97    45.1 1807.06    53.4 1805.72    61.7 1805.07
    74.1 1804.63    82.4 1804.79    99.1 1806.22   119.8 1806.69   140.6 1807.84
   169.8  1808.6   178.2 1808.12   182.5 1806.53   186.7 1802.97  190.09 1801.94
   195.2 1801.49   210.9 1801.95   224.9  1803.9   233.3 1803.85   241.8 1805.26
     246  1805.6     263 1804.01   271.5 1805.19   284.2 1804.23   288.4 1805.07
   292.7 1806.87   301.1 1811.92   309.6 1815.92   318.1 1818.43   325.6 1819.35
#Mann= 3 ,-1,0
       0      .1       0  190.09    .045       0   210.9      .1       0
#XS Ineff= 2 , 0
                          276.84          1806.4
Permanent Ineff=
       F       F
Bank Sta=190.09,210.9
XS Rating Curve= 0 ,0
Exp/Cntr(USF)=0,0
Exp/Cntr=0.3,0.1

Type RM Length L Ch R = 1 ,843     ,193.8,190,189.5
XS GIS Cut Line= 3
 2237586.1404724726844.6629886872237703.15162618726487.628955351
2237590.64090139726462.876595897
#Sta/Elev= 30
       0 1819.74     3.7 1818.75     7.9 1817.09    28.9 1806.05    33.1 1804.67
    36.1 1804.39    61.4 1804.21    79.4 1804.76   102.7 1802.91   113.1 1803.26
   124.8 1804.43   134.2 1804.84   188.3 1804.76   205.7 1805.28   214.1 1804.66
   226.8 1801.53   264.6 1802.71   273.1  1802.4   277.3 1801.45  280.811799.816
   285.7 1799.21   292.9  1799.3  296.921799.827   306.7 1801.23   336.2 1802.56
   407.1 1803.84   427.3 1806.25   444.3 1809.83   467.6 1810.28   490.9 1812.42
#Mann= 4 ,-1,0
       0     .06       0      20      .1       0  280.81    .045       0
  296.92      .1       0
#XS Ineff= 2 , 0
          137.31 1807.65
Permanent Ineff=
       F       F
Bank Sta=280.81,296.92
XS Rating Curve= 0 ,0
Exp/Cntr(USF)=0,0
Exp/Cntr=0.3,0.1

Type RM Length L Ch R = 1 ,653     ,33.4,33.2,33
XS GIS Cut Line= 5
2237727.52894989726927.9959321822237790.53495577726839.487495346
2237760.53209582726731.4771995472237747.03080885726625.717118244
2237800.28588525726449.450316072
#Sta/Elev= 30
       0 1815.19      14 1812.81    19.7 1810.91    36.9 1803.48    42.6 1801.57
    47.6 1800.86   148.2 1800.82   161.2 1801.38     219 1800.42   247.3 1801.22
   251.3 1801.11  258.671798.333   263.4 1797.56   269.81798.297   275.5 1799.71
   279.5 1800.13   294.6 1800.02   327.4 1801.86   369.7 1800.75   386.4    1801
     399 1801.97   414.3 1801.43   432.4 1801.64     442 1801.96   457.5 1803.35
   465.8 1803.03   482.5 1803.34     486 1804.29   490.9 1807.05   511.5 1807.84
#Mann= 4 ,-1,0
       0     .06       0      10      .1       0  258.67    .045       0
   269.8      .1       0
#XS Ineff= 2 , 0
          248.02 1803.47  319.47         1803.09
Permanent Ineff=
       F       F
Bank Sta=258.67,269.8
XS Rating Curve= 0 ,0
Exp/Cntr(USF)=0,0
Exp/Cntr=0.3,0.1

Type RM Length L Ch R = 1 ,620     ,206,218.8,228.6
XS GIS Cut Line= 5
2237760.15706008 726923.495503192237823.16306596726834.987066355
2237793.16020601726726.9767705562237779.65891904726621.216689253
2237832.91399544726444.949887081
#Sta/Elev= 30
       0 1806.16     6.9 1803.55    12.7 1802.08    24.6 1800.74    56.9 1800.81
    76.5 1801.64   102.1 1801.42   127.1 1801.84   139.6 1800.84   172.8 1800.15
   201.9 1801.27   238.7 1801.69   242.7 1801.49  252.74 1798.57   262.9 1797.57
   266.9 1797.69  269.431798.552     275 1800.41   294.8 1801.85   323.3 1800.84
   366.3  1801.3   381.7 1801.03   415.2 1802.11   444.4 1804.61   461.1 1804.25
   469.5 1803.48   473.7 1804.66   477.8 1807.58     482 1809.05   511.5 1809.76
#Mann= 4 ,-1,0
       0      .1       0  252.74    .045       0  269.43      .1       0
   511.5     .06       0
#XS Ineff= 2 , 0
           89.77    1803  297.03         1802.74
Permanent Ineff=
       F       F
Bank Sta=252.74,269.43
XS Rating Curve= 0 ,0
Exp/Cntr(USF)=0,0
Exp/Cntr=0.3,0.1

Type RM Length L Ch R = 1 ,401     ,258.3,258.3,258.3
XS GIS Cut Line= 3
2237748.53609637726980.1408204532237977.30790344726735.617511907
2237979.55811794726617.106215128
#Sta/Elev= 30
       0 1815.69    31.4 1810.48    36.9 1809.17    52.2 1804.19    69.7 1801.28
    97.2 1800.95   108.1 1801.87   120.7 1802.11   180.1 1799.72   195.8 1798.76
   212.2 1798.78   228.2 1799.69   234.1 1799.18   245.2 1799.58   253.7 1798.88
     267  1798.8   268.8 1798.26  274.221795.515   279.2 1794.65  285.641795.544
   294.4 1797.78   307.5 1798.34   321.5 1799.69   324.5 1800.42   332.9 1803.51
   341.3 1804.43   354.8  1808.1   361.3 1809.26   393.3 1811.76   453.4 1812.78
#Mann= 5 ,-1,0
       0      .1       0     130     .06       0     270      .1       0
  274.22    .045       0  285.64      .1       0
#XS Ineff= 2 , 0
          244.79 1801.98
Permanent Ineff=
       F       F
Bank Sta=274.22,285.64
XS Rating Curve= 0 ,0
Exp/Cntr(USF)=0,0
Exp/Cntr=0.3,0.1

Type RM Length L Ch R = 1 ,143     ,,,
XS GIS Cut Line= 4
2237767.58823226727116.277406523 2238058.7682516726968.115135193
2238078.46274867726848.6052764762238063.41208097726777.923794654
#Sta/Elev= 30
       0 1817.03    23.1 1812.02    32.1 1811.71    72.5 1807.28    94.9 1806.41
   103.9    1805   117.3 1804.45   136.6 1802.17   157.4  1802.5   184.7 1805.77
   207.1 1806.16   211.6 1805.04   213.6 1803.86   220.6 1797.88   225.1 1795.23
   238.5 1794.26  242.671795.231     252    1797   283.4 1796.81   291.3 1797.38
   301.4 1799.84   319.3 1806.31   330.5 1807.59   345.9 1808.04   354.8 1807.07
   402.7 1807.12     431 1805.21   475.9 1809.98   503.2  1811.3   520.1 1811.41
#Mann= 4 ,-1,0
       0     .06       0     190      .1       0   225.1    .045       0
  242.67      .1       0
Bank Sta=225.1,242.67
XS Rating Curve= 0 ,0
Exp/Cntr(USF)=0,0
Exp/Cntr=0.3,0.1
LCMann Table=0

Chan Stop Cuts=-1
Use User Specified Reach Order=0
Composite Channel Slope=5